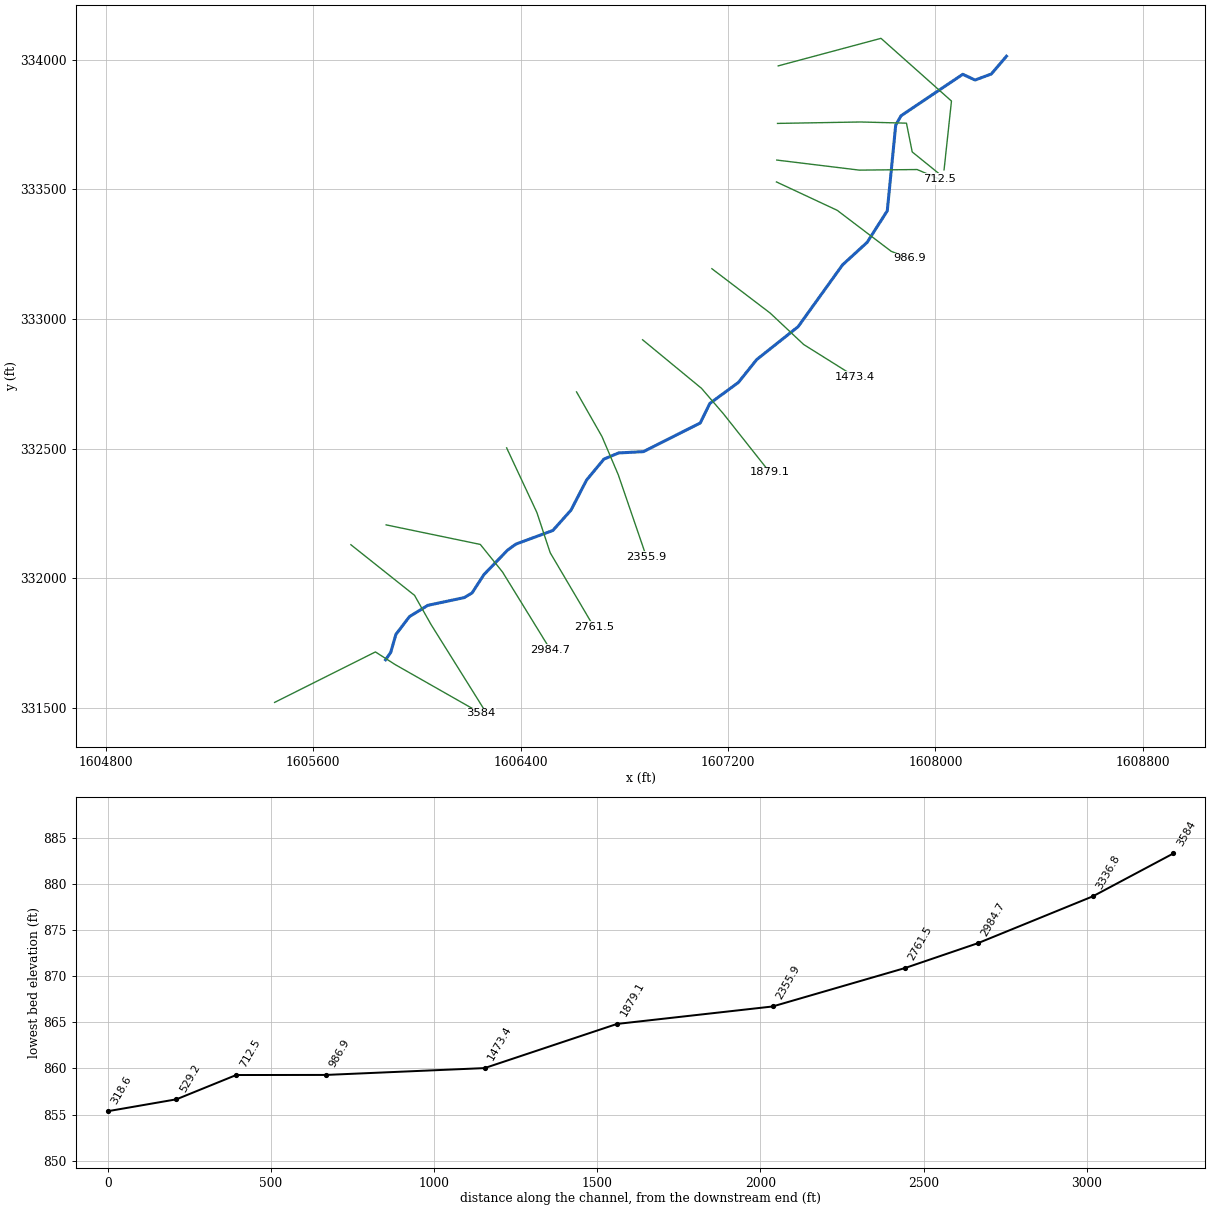
--- pnmthbrnch.prj (project) ---

Proj Title=pnmthbrnch
Current Plan=p01
Default Exp/Contr=0,0
English Units
Geom File=g01
Flow File=f01
Plan File=p01
BEGIN DESCRIPTION:
END DESCRIPTION:
DSS Export Rating Curves= 0
DSS Export Rating Curve Sorted= 0
DSS Export Volume Flow Curves= 0
DXF OffsetX= 0
DXF OffsetY= 0
DXF ScaleX= 0
DXF ScaleY= 0

--- pnmthbrnch.p01 (plan) ---

Plan Title=Floodplain
Program Version=4.00
Geom File=g01
Flow File=f01
K Sum by GR=0
Std Step Tol=0.01
Critical Tol=0.01
Num of Std Step Trials=20
Max Error Tol=0.3
Flow Tol Ratio=0.001
Split Flow NTrial=30
Split Flow Tol=0.02
Split Flow Ratio=0.02
Log Output Level=0
Friction Slope Method=1
Unsteady Friction Slope Method=2
Unsteady Bridges Friction Slope Method=1
Global Log Level=0
CheckData=False
Run HTab=0
Run UNet=0
Run PostProcess=0
UNET Theta=0
UNET Theta Warmup=0
UNET ZTol=0
UNET ZSATol=0
UNET MxIter=0
UNET MaxInSteps=0
UNET DtIC=0
UNET DtMin=0
UNET MaxCRTS=0
UNET WFStab=0
UNET SFStab=0
UNET WFX=0
UNET SFX=0
UNET DSS MLevel=0
UNET DZMax Abort=0
UNET Convert EG Bridges=0
UNET Use Existing IB Tables=0
UNET Froude Limit=0
UNET Froude Power=0
Write IC File=0
Echo Input=False
Echo Output=False
Write Detailed=0

--- pnmthbrnch.f01 (steady flow) ---

Flow Title=NFF Regression Equation
Program Version=4.00
Number of Profiles= 1
Profile Names=P100yr
River Rch & RM=pnmthbrnch,Main            ,3584
     538
Boundary for River Rch & Prof#=pnmthbrnch,Main            , 1
Up Type= 0
Dn Type= 3
Dn Slope=0.004
DSS Import GetInterval= 0
DSS Import GetPeak= 0
DSS Import FillOption= 0

--- pnmthbrnch.g01 (geometry) ---

Geom Title=USGS 10m DEM
Program Version=4.00

River Reach=pnmthbrnch      ,Main
Reach XY= 30
     1605879.467      331686.347     1605899.146      331714.284
     1605919.443      331784.214     1605971.597      331852.736
     1606042.422      331896.218     1606183.005      331926.058
     1606213.095      331944.087     1606258.696       332014.59
     1606350.142      332109.319     1606382.235      332132.449
     1606524.574      332184.854     1606594.663      332263.512
     1606654.515      332379.181     1606721.587      332460.139
     1606778.259      332483.853     1606873.762      332488.971
     1607093.064      332599.372     1607129.829      332674.758
     1607239.945      332755.563     1607310.743       332843.98
      1607470.48      332970.879     1607641.873      333209.278
     1607736.738       333296.15     1607814.333      333417.715
     1607846.884      333748.359     1607867.442      333784.336
     1608105.431      333944.148     1608153.017      333922.078
     1608215.531       333945.35       1608273.9      334013.677

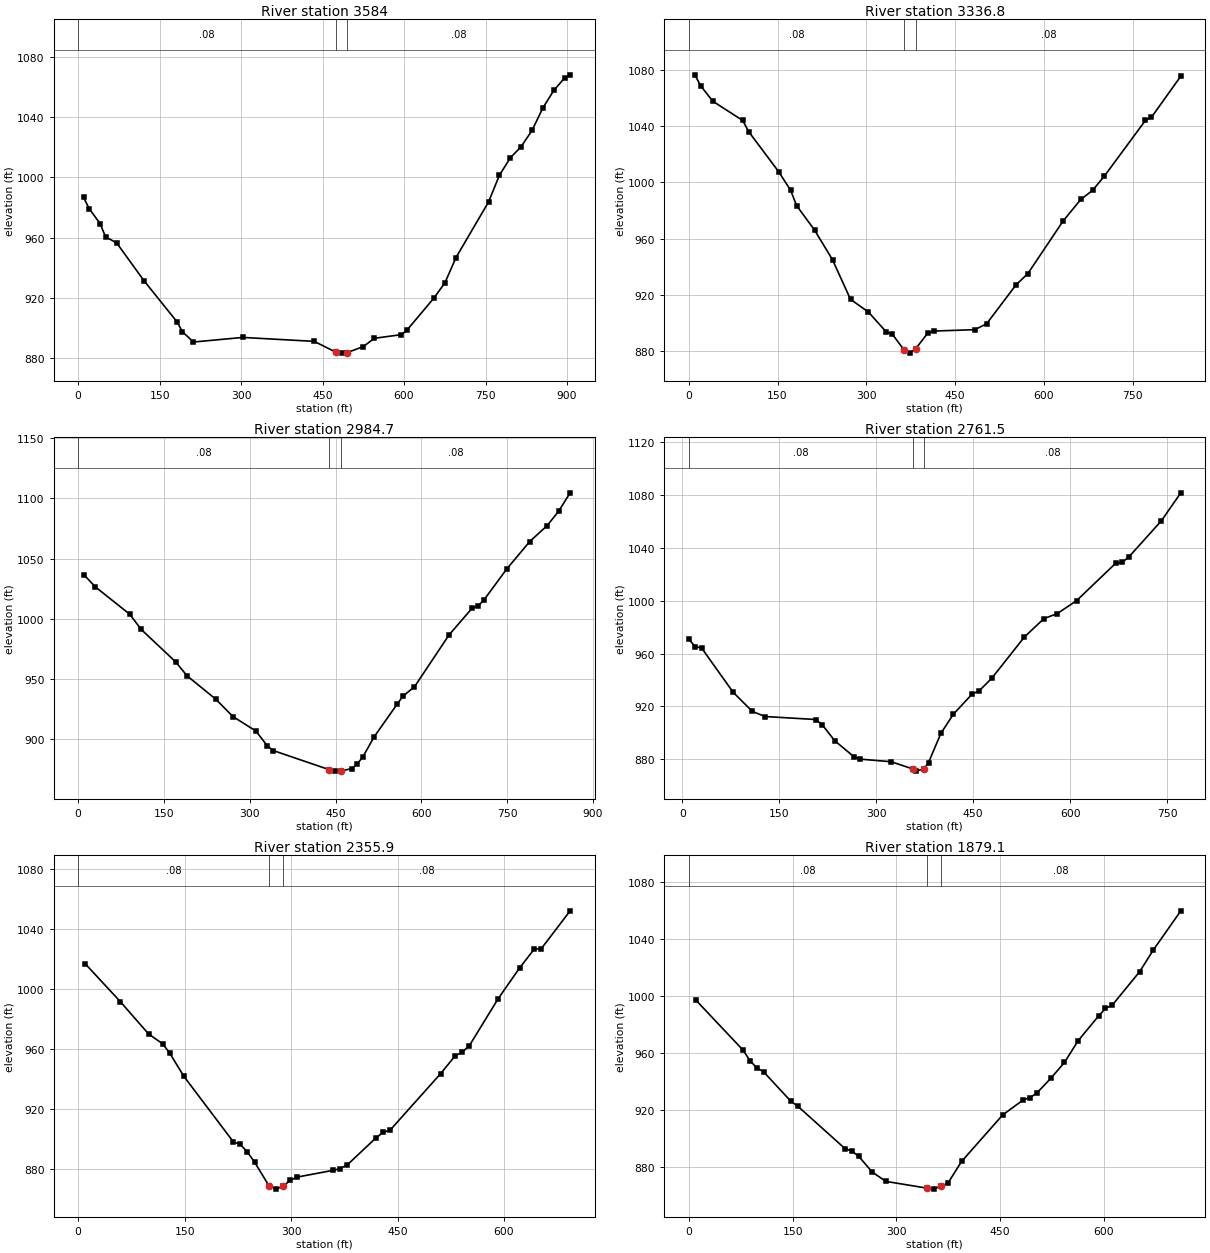
Type RM Length L Ch R = 1 ,3584    ,259.4,247.2,235
XS GIS Cut Line= 4
     1605451.665      331521.905     1605840.367      331716.494
     1605916.604      331667.668     1606247.438      331479.551
#Sta/Elev= 30
    10.1   986.6    20.2  979.26    40.4  969.24    50.5  960.45    70.8   956.5
   121.3  931.32     182  904.07   192.1  897.43   212.3  890.65   303.3   893.7
   434.7  891.08     475  883.82     485  883.28     495   883.6   525.2  887.66
   545.3  893.12   595.3  895.56   605.3  898.49   655.4  920.02   675.4  930.06
   695.5  946.61   755.6  983.64   775.6 1001.35   795.6 1012.85   815.7 1020.41
   835.7 1031.11   855.7 1046.12   875.8 1057.67   895.8 1066.01   905.8 1067.99
#Mann= 3 , 0 , 0
       0     .08       0     475    .045       0     495     .08       0
Bank Sta=475,495
XS Rating Curve= 0 ,0
Exp/Cntr=0.3,0.1

Type RM Length L Ch R = 1 ,3336.8  ,347.8,352,356.2
XS GIS Cut Line= 4
     1605745.666      332129.989     1605991.222      331934.686
     1606055.181      331821.616     1606260.763      331492.685
#Sta/Elev= 30
    10.1 1076.22    20.2 1068.33    40.5 1057.48    91.1  1043.8   101.2 1035.91
   151.8 1007.47   172.1  994.21   182.2  983.36   212.5  966.02   242.9   944.9
   273.3  916.82   303.6  907.79   333.7  893.69   343.7  892.22   363.7  880.96
   373.7  878.63   383.7  881.88   403.7  892.76   413.7   894.3   483.4  895.28
   503.3  899.45   553.1  927.12     573  935.06   632.6   972.4   662.5  987.74
   682.4  994.17   702.3 1004.25   771.9 1043.91   781.8 1045.99   831.6 1075.26
#Mann= 3 , 0 , 0
       0     .08       0   363.7    .045       0   383.7     .08       0
Bank Sta=363.7,383.7
XS Rating Curve= 0 ,0
Exp/Cntr=0.3,0.1

Type RM Length L Ch R = 1 ,2984.7  ,232.3,223.3,214.3
XS GIS Cut Line= 4
     1605881.579      332206.511     1606244.773      332131.131
     1606330.432      332024.914     1606515.456      331724.536
#Sta/Elev= 30
      10 1036.58    30.1 1026.46    90.2 1003.76   110.3  991.14   170.4  964.28
   190.5  952.63   240.6  933.26   270.7  918.83   310.8  906.84   330.8  894.49
   340.9  890.66   438.9  874.79   448.9  873.56   458.9  873.68   478.1   875.6
   487.9  879.48   497.6  885.24   517.5  902.01   557.8  929.16   567.9  935.83
     588  943.51   648.5   986.6   688.8 1008.79   698.9 1010.59     709 1015.31
   749.3 1041.29   789.6 1064.13   819.9 1077.27     840  1089.2   860.2 1104.53
#Mann= 3 , 0 , 0
       0     .08       0   438.9    .045       0   458.9     .08       0
Bank Sta=438.9,458.9
XS Rating Curve= 0 ,0
Exp/Cntr=0.3,0.1

Type RM Length L Ch R = 1 ,2761.5  ,403.5,405.6,407.8
XS GIS Cut Line= 4
     1606346.422      332503.463     1606462.918       332254.48
     1606514.314      332099.152     1606683.348      331812.479
#Sta/Elev= 30
     9.8  970.89    19.6  965.23    29.5  964.24    78.5  930.58     108  916.19
   127.6  912.26   206.2  909.98     216  906.19   235.6  893.93   265.1  881.88
   274.9  879.97     323  877.99  356.76  872.47   361.5  870.87  373.52  872.53
   380.8  877.36     400  899.54   419.3     914   448.6  929.42   458.7  931.46
   478.8  941.31   529.3  972.56   559.5  986.48   579.7  990.14   609.9 1000.01
   670.4 1028.35   680.5 1029.05   690.6 1033.02     741 1060.44   771.3 1081.76
#Mann= 3 , 0 , 0
     9.8     .08       0  356.76    .045       0  373.52     .08       0
Bank Sta=356.76,373.52
XS Rating Curve= 0 ,0
Exp/Cntr=0.3,0.1

Type RM Length L Ch R = 1 ,2355.9  ,468.8,476.8,484.7
XS GIS Cut Line= 4
     1606615.962      332719.324     1606714.185      332546.863
     1606777.002       332399.53     1606885.503      332083.162
#Sta/Elev= 30
     9.9 1016.98    59.5  991.67    99.2  970.17   119.1  963.59     129  957.35
   148.9  941.95   218.5  898.32   228.5   896.5   238.5  891.39   248.5  884.75
   268.6  869.12   278.6  866.71   288.6  868.67   298.6  872.47   308.6  874.74
   358.6  879.19   368.8  880.37   378.9  882.77   419.4   900.8   429.6   904.5
   439.7  906.16   510.7  943.73   530.9  955.45   541.1  958.03   551.2   962.4
   591.7  993.68   622.1  1014.3   642.4 1026.66   652.6 1027.11   693.1 1052.25
#Mann= 3 , 0 , 0
       0     .08       0   268.6    .045       0   288.6     .08       0
Bank Sta=268.6,288.6
XS Rating Curve= 0 ,0
Exp/Cntr=0.3,0.1

Type RM Length L Ch R = 1 ,1879.1  ,402.9,405.6,408.3
XS GIS Cut Line= 4
     1606870.656      332920.337     1607097.938      332733.029
     1607182.455      332634.807     1607360.626      332409.809
#Sta/Elev= 30
     9.8  997.31    78.5  962.06    88.4  954.73    98.2   949.7     108  946.95
   147.3  926.43   157.1  923.03   225.8  893.15   235.6  891.45   245.4  887.86
   265.1  876.78   284.7  870.25   344.3  865.49   354.3  864.82   364.3  867.08
   374.3  868.86   394.2  884.17   453.8  916.84   483.5  927.31   493.4  928.89
   503.3  932.23   523.1  942.33   542.9  953.46   562.6  968.62   592.3  986.08
   602.2  991.26   612.1  993.63   651.7 1017.09   671.5 1032.29   711.1 1059.61
#Mann= 3 , 0 , 0
       0     .08       0   344.3    .045       0   364.3     .08       0
Bank Sta=344.3,364.3
XS Rating Curve= 0 ,0
Exp/Cntr=0.3,0.1

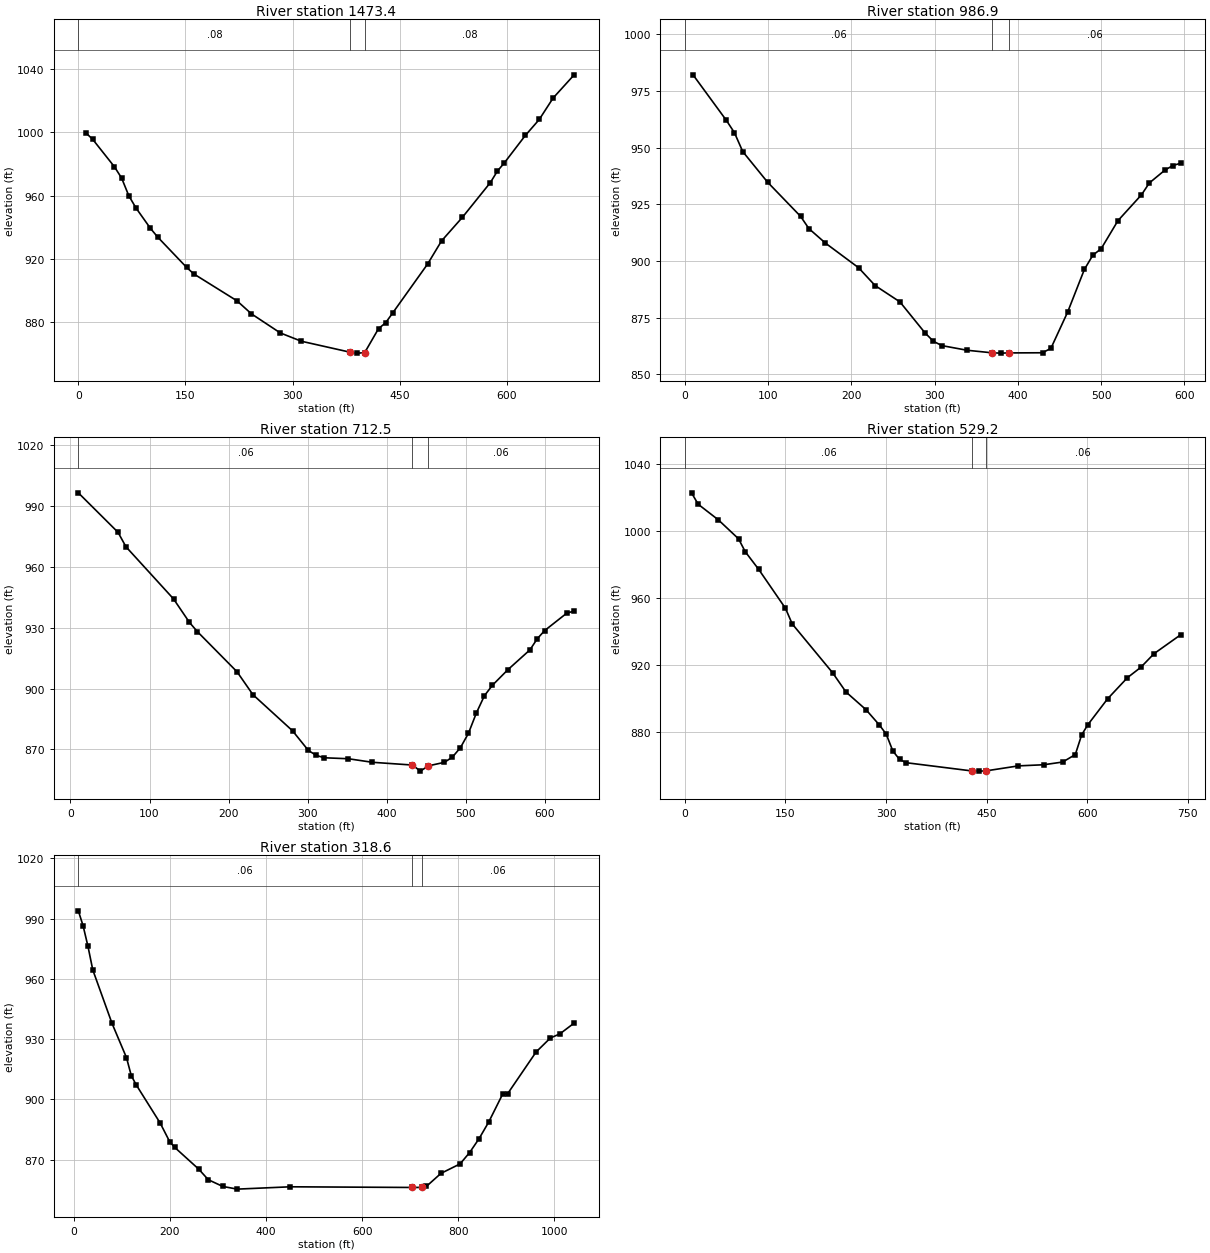
Type RM Length L Ch R = 1 ,1473.4  ,483.8,486.5,489.2
XS GIS Cut Line= 4
     1607137.912      333194.446      1607362.91      333023.128
      1607491.97      332902.063     1607690.699      332777.572
#Sta/Elev= 30
    10.1  999.96    20.2  995.58    50.5  978.26    60.6  971.09    70.7  959.83
    80.8  952.06     101  939.16   111.1  933.65   151.5  914.47   161.6  910.31
   222.2   893.2   242.4  884.95   282.8  872.85   312.3  867.58   380.9  860.59
   390.9  860.04   400.9   860.3   420.4   875.6   430.3  879.28   440.1  885.45
   489.1  916.56   508.6  931.21   537.9  946.22     577  968.24   586.8  975.49
   596.5  980.69   625.9  998.08   645.4 1008.22   664.9 1021.87   694.3 1036.55
#Mann= 3 , 0 , 0
       0     .08       0   380.9    .045       0   400.9     .08       0
Bank Sta=380.9,400.9
XS Rating Curve= 0 ,0
Exp/Cntr=0.3,0.1

Type RM Length L Ch R = 1 ,986.9   ,257.6,274.5,291.4
XS GIS Cut Line= 4
     1607386.894      333529.088     1607621.029       333419.73
     1607829.657      333261.356     1607899.707      333233.945
#Sta/Elev= 30
     9.9  982.07    49.7   962.1    59.6  956.57    69.6  948.22    99.4  934.73
   139.1  919.63   149.1  914.22     169  907.82   208.7  896.99   228.6  889.11
   258.4  881.91   288.6  868.21   298.7  864.51   308.8  862.62     339  860.57
   369.3  859.43   379.3   859.3   389.3  859.39   429.7  859.46   439.8  861.43
   459.9  877.42     480  896.23   490.1  902.47   500.2  905.39   520.3  917.73
   548.6  929.15     558  934.36   576.8  940.05   586.2  942.04   595.6  943.08
#Mann= 3 , 0 , 0
       0     .06       0   369.3    .045       0   389.3     .06       0
Bank Sta=369.3,389.3
XS Rating Curve= 0 ,0
Exp/Cntr=0.3,0.1

Type RM Length L Ch R = 1 ,712.5   ,183.2,183.2,183.2
XS GIS Cut Line= 4
     1607388.037      333613.446     1607706.688      333574.614
     1607929.402      333576.898     1608015.061       333540.35
#Sta/Elev= 30
      10  996.61    60.2  977.12    70.2     970   130.4  944.25   150.5  932.67
   160.5  928.13   210.7  908.29   230.7  897.04   280.9  879.16   300.9  869.47
     311  867.03     321  865.88   351.4   865.4   381.8  863.65   432.5  862.29
   442.5  859.29   452.5  861.88   472.9  863.64     483  866.22   493.1  870.87
   503.2  877.92   513.4   888.1   523.5  896.54   533.6  901.67     553   909.3
     581  919.13   590.3  924.63   599.6  928.65   627.6  937.25   636.9  938.28
#Mann= 3 , 0 , 0
      10     .06       0   432.5    .045       0   452.5     .06       0
Bank Sta=432.5,452.5
XS Rating Curve= 0 ,0
Exp/Cntr=0.3,0.1

Type RM Length L Ch R = 1 ,529.2   ,229.6,210.7,191.7
XS GIS Cut Line= 5
     1607391.082      333754.752     1607711.257      333760.272
     1607888.286      333755.704     1607910.469      333644.786
     1608010.493      333563.827
#Sta/Elev= 30
      10 1023.06      20 1016.21      50  1006.9    80.1  995.57    90.1  987.86
   110.1  977.32   150.1  953.99   160.1  944.69   220.2  915.55   240.2  904.01
   270.2  893.37   290.2  884.17   300.2  878.81   310.2  868.65   320.2  863.63
   330.1  861.69   428.3  856.75   438.3  856.66   448.3  856.77   497.3   859.8
     535  860.47   563.3   862.1   582.1  866.56   591.6  878.37     601  884.51
   630.2  899.88   659.9  912.57   679.7  918.71   699.5   926.9   739.1  938.17
#Mann= 3 , 0 , 0
       0     .06       0   428.3    .045       0   448.3     .06       0
Bank Sta=428.3,448.3
XS Rating Curve= 0 ,0
Exp/Cntr=0.3,0.1

Type RM Length L Ch R = 1 ,318.6   ,319.3,318.6,317.5
XS GIS Cut Line= 4
     1607393.747      333976.641     1607790.063      334082.858
     1608061.888      333841.014     1608033.335      333575.724
#Sta/Elev= 30
      10  993.88      20  986.35      30  976.23      40  964.52    80.1  937.83
   110.1  920.83   120.1  911.86   130.1  907.36   180.1  888.29   200.1  878.92
   210.2  876.19   260.2  865.35   280.2  860.06   310.2  856.72   340.3  855.37
   450.7  856.53   703.4   856.2  725.47  856.22   733.7  856.72     764  863.21
   803.8  867.93   823.6  873.56   843.3   880.5   863.1  888.66   892.7  902.85
   902.6  902.83   961.9  923.64   991.5  930.58  1011.3  932.64    1041  938.01
#Mann= 3 , 0 , 0
      10     .06       0   703.4    .045       0  725.47     .06       0
#XS Ineff= 2 , 0
       0     490                       0
Permanent Ineff=
       F       F
Bank Sta=703.4,725.47
XS Rating Curve= 0 ,0
Exp/Cntr=0.3,0.1

Chan Stop Cuts=-1
Use User Specified Reach Order=0